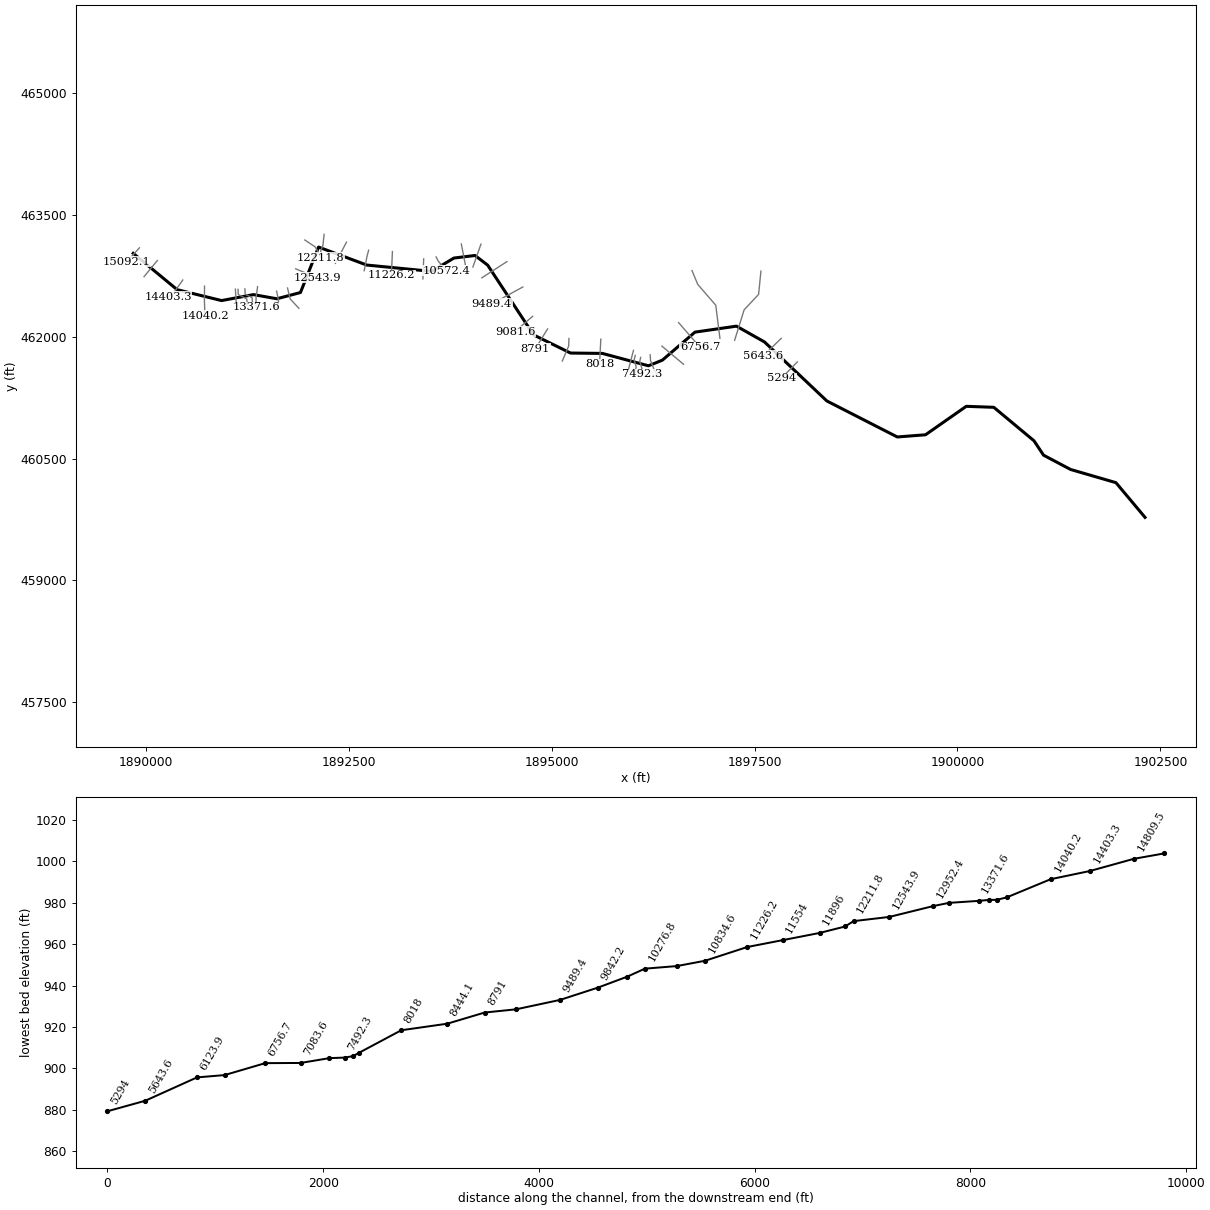
--- BELLSCK.prj (project) ---

Proj Title=BELLSCK
Current Plan=p01
Default Exp/Contr=0,0
English Units
Geom File=g01
Flow File=f01
Plan File=p01
BEGIN DESCRIPTION:
END DESCRIPTION:
DSS Export Rating Curves= 0
DSS Export Rating Curve Sorted= 0
DSS Export Volume Flow Curves= 0
DXF OffsetX= 0
DXF OffsetY= 0
DXF ScaleX= 0
DXF ScaleY= 0

--- BELLSCK.p01 (plan) ---

Plan Title=Floodplain
Program Version=4.00
Geom File=g01
Flow File=f01
K Sum by GR=0
Std Step Tol=0.01
Critical Tol=0.01
Num of Std Step Trials=20
Max Error Tol=0.3
Flow Tol Ratio=0.001
Split Flow NTrial=30
Split Flow Tol=0.02
Split Flow Ratio=0.02
Log Output Level=0
Friction Slope Method=1
Unsteady Friction Slope Method=2
Unsteady Bridges Friction Slope Method=1
Global Log Level=0
CheckData=False
Run HTab=0
Run UNet=0
Run PostProcess=0
UNET Theta=0
UNET Theta Warmup=0
UNET ZTol=0
UNET ZSATol=0
UNET MxIter=0
UNET MaxInSteps=0
UNET DtIC=0
UNET DtMin=0
UNET MaxCRTS=0
UNET WFStab=0
UNET SFStab=0
UNET WFX=0
UNET SFX=0
UNET DSS MLevel=0
UNET DZMax Abort=0
UNET Convert EG Bridges=0
UNET Use Existing IB Tables=0
UNET Froude Limit=0
UNET Froude Power=0
Write IC File=0
Echo Input=False
Echo Output=False
Write Detailed=0

--- BELLSCK.f01 (steady flow) ---

Flow Title=NFF Regression Equation
Program Version=4.10
Number of Profiles= 1
Profile Names=P100yr
River Rch & RM=BELLSCK,Main            ,15092.1
576.3288
River Rch & RM=BELLSCK,Main            ,14403.3
582.8221
River Rch & RM=BELLSCK,Main            ,14040.2
728.7719
River Rch & RM=BELLSCK,Main            ,12543.9
 768.223
River Rch & RM=BELLSCK,Main            ,11896
831.3993
River Rch & RM=BELLSCK,Main            ,8018
911.1415
River Rch & RM=BELLSCK,Main            ,6379.3
1011.115
River Rch & RM=BELLSCK,Main            ,6123.9
1469.226
River Rch & RM=BELLSCK,Main            ,277.7
 1620.23
Boundary for River Rch & Prof#=BELLSCK,Main            , 1
Up Type= 0
Dn Type= 3
Dn Slope=0.01
DSS Import GetInterval= 0
DSS Import GetPeak= 0
DSS Import FillOption= 0

--- BELLSCK.g01 (geometry) ---

Geom Title=USGS 10m DEM
Program Version=4.10

River Reach=BELLSCK         ,Main
Reach XY= 30
     1889843.828       463029.76     1890385.364      462582.161
     1890932.934      462447.786     1891325.691      462521.247
     1891614.097      462470.008     1891904.765      462546.918
     1892127.865      463106.824     1892720.782      462885.476
     1893520.855        462807.4      1893795.83      462971.663
     1894055.981      463003.183     1894211.189      462884.433
     1894776.814      462025.058     1895232.196      461801.446
      1895624.21      461796.933     1896192.265      461644.502
      1896364.14      461713.946     1896765.646      462059.136
     1897276.901      462132.696      1897622.14      461938.092
     1898390.529      461211.151     1899258.268       460767.73
     1899606.154      460794.658     1900108.081      461145.153
     1900447.473      461133.109     1900942.695      460720.739
     1901060.776      460543.236     1901393.955       460367.29
     1901952.446      460204.884     1902310.784      459777.376

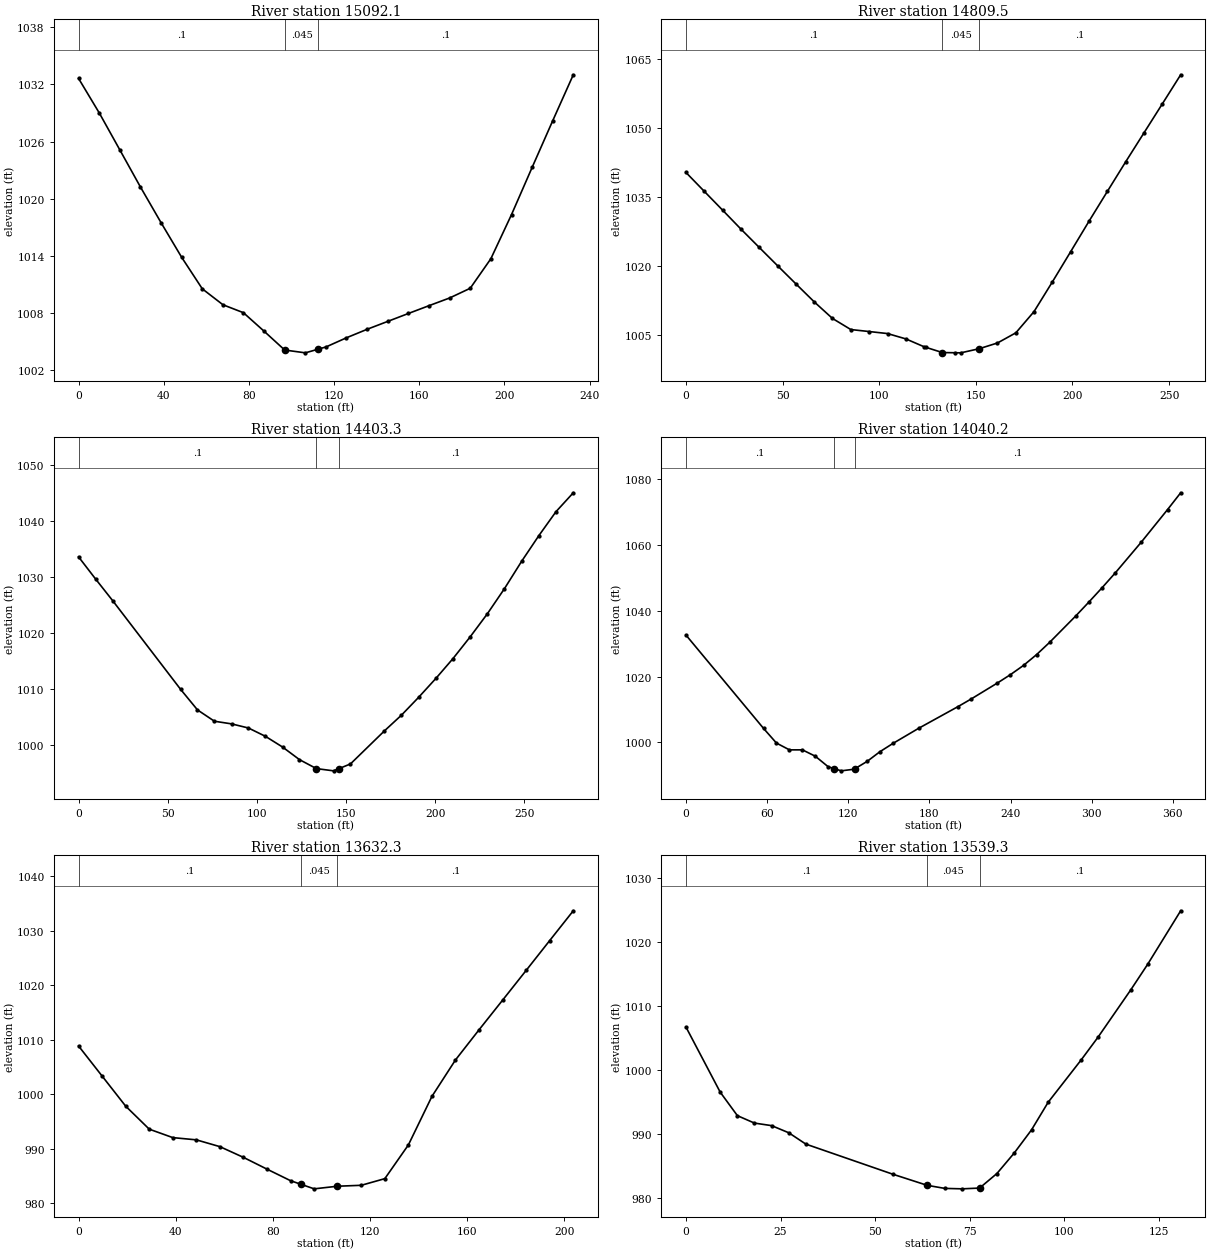
Type RM Length L Ch R = 1 ,15092.1 ,281.6,282.6,283.6
XS GIS Cut Line= 2
     1889920.703       463097.41     1889763.906      462926.002
#Sta/Elev= 27
       0 1032.62     9.7 1029.01    19.4 1025.12      29 1021.26    38.7 1017.51
    48.4 1013.87    58.1 1010.56    67.8 1008.89    77.4 1008.06    87.1 1006.12
    96.8 1004.14    97.6 1004.12   106.5 1003.85   112.6 1004.24   116.2 1004.47
   125.8 1005.43   135.5 1006.32   145.2 1007.15   154.9 1007.98   164.6  1008.8
   174.2  1009.6   183.9 1010.62   193.6 1013.72   203.3 1018.35     213 1023.31
   222.6 1028.17   232.3 1033.01
#Mann= 3 , 0 , 0
       0      .1       0    96.8    .045       0   112.6      .1       0
Bank Sta=96.8,112.6
XS Rating Curve= 0 ,0
Exp/Cntr=0.3,0.1

Type RM Length L Ch R = 1 ,14809.5 ,404.4,406.2,407.8
XS GIS Cut Line= 2
     1890140.915      462940.178     1889977.721      462742.956
#Sta/Elev= 30
       0 1040.33     9.5 1036.23      19 1032.14    28.4 1028.07    37.9 1024.08
    47.4 1020.11    56.9 1016.17    66.4 1012.26    75.8 1008.68    85.3 1006.27
    94.8 1005.84   104.3  1005.4   113.8 1004.24   123.2 1002.54   124.4 1002.38
   132.7 1001.28   139.4 1001.24   142.2 1001.22   151.7 1002.11   161.2 1003.36
   170.7 1005.56   180.1 1010.16   189.6  1016.6   199.1 1023.18   208.6 1029.79
   218.1 1036.26   227.5 1042.62     237 1048.92   246.5 1055.21     256 1061.52
#Mann= 3 , 0 , 0
       0      .1       0   132.7    .045       0   151.7      .1       0
Bank Sta=132.7,151.7
XS Rating Curve= 0 ,0
Exp/Cntr=0.3,0.1

Type RM Length L Ch R = 1 ,14403.3 ,349.2,363.1,376.6
XS GIS Cut Line= 3
     1890455.085      462701.356     1890350.226      462553.732
     1890274.862      462493.634
#Sta/Elev= 27
       0 1033.52     9.5 1029.59    19.1 1025.72    57.2  1009.9    66.7 1006.22
    76.2  1004.2    85.8 1003.73    95.3 1002.99   104.8 1001.51   114.4   999.6
   123.9  997.35   133.4  995.75     143  995.35   146.1  995.75   152.5  996.58
   171.5 1002.46   181.1 1005.28   190.7 1008.45   200.4 1011.83     210 1015.37
   219.6 1019.23   229.3 1023.37   238.9 1027.86   248.6 1032.77   258.2 1037.32
   267.8 1041.59   277.5 1044.96
#Mann= 3 , 0 , 0
       0      .1       0   133.4    .045       0   146.1      .1       0
Bank Sta=133.4,146.1
XS Rating Curve= 0 ,0
Exp/Cntr=0.3,0.1

Type RM Length L Ch R = 1 ,14040.2 ,405.8,407.9,409.1
XS GIS Cut Line= 3
     1890722.996      462625.361     1890721.124      462453.247
     1890728.136      462259.717
#Sta/Elev= 29
       0 1032.56    57.4 1004.24    66.9  999.82    76.5  997.76    86.1  997.76
    95.6  995.84   105.2  992.62   109.7  992.05   114.8   991.4   124.3  991.89
   124.7  991.99   133.9  994.25   143.4   997.2     153   999.7   172.1 1004.31
   201.2 1010.89   210.9 1013.19   230.2 1018.01   239.9 1020.56   249.6 1023.37
   259.3 1026.66     269  1030.4   288.3  1038.4     298 1042.61   307.7 1046.93
   317.4  1051.4   336.7 1060.76   356.1 1070.62   365.8 1075.71
#Mann= 3 , 0 , 0
       0      .1       0   109.7    .045       0   124.7      .1       0
Bank Sta=109.7,124.7
XS Rating Curve= 0 ,0
Exp/Cntr=0.3,0.1

Type RM Length L Ch R = 1 ,13632.3 ,50.4,93,128.7
XS GIS Cut Line= 2
     1891102.946      462588.749     1891114.987      462385.403
#Sta/Elev= 23
       0 1008.82     9.7  1003.3    19.4  997.78    29.1  993.56    38.8  992.01
    48.5   991.6    58.2  990.35    67.9  988.38    77.6  986.22    87.3   984.1
    91.6  983.44      97  982.61   106.6  983.09   116.4  983.26   126.1  984.48
   135.8  990.67   145.5  999.58   155.2 1006.27   164.9  1011.8   174.6 1017.24
   184.3  1022.7     194 1028.18   203.7 1033.64
#Mann= 3 , 0 , 0
       0      .1       0    91.6    .045       0   106.6      .1       0
Bank Sta=91.6,106.6
XS Rating Curve= 0 ,0
Exp/Cntr=0.3,0.1

Type RM Length L Ch R = 1 ,13539.3 ,86.1,72.2,61.9
XS GIS Cut Line= 4
     1891135.585      462585.971     1891138.404      462522.624
     1891243.933      462466.715     1891249.474      462388.054
#Sta/Elev= 21
       0 1006.72    9.05  996.54    13.6  992.86    18.1   991.7   22.65   991.3
    27.2  990.18    31.7  988.41   54.65  983.71    63.8  981.96   68.45  981.48
   73.05  981.41   77.65  981.53   82.25  983.81    86.8     987    91.4  990.64
    95.8  994.96  104.55  1001.6  108.95 1005.11   117.7 1012.59   122.1 1016.53
  130.85 1024.92
#Mann= 3 , 0 , 0
       0      .1       0    63.8    .045       0   77.65      .1       0
Bank Sta=63.8,77.65
XS Rating Curve= 0 ,0
Skew Angle= 60
Exp/Cntr=0.3,0.1

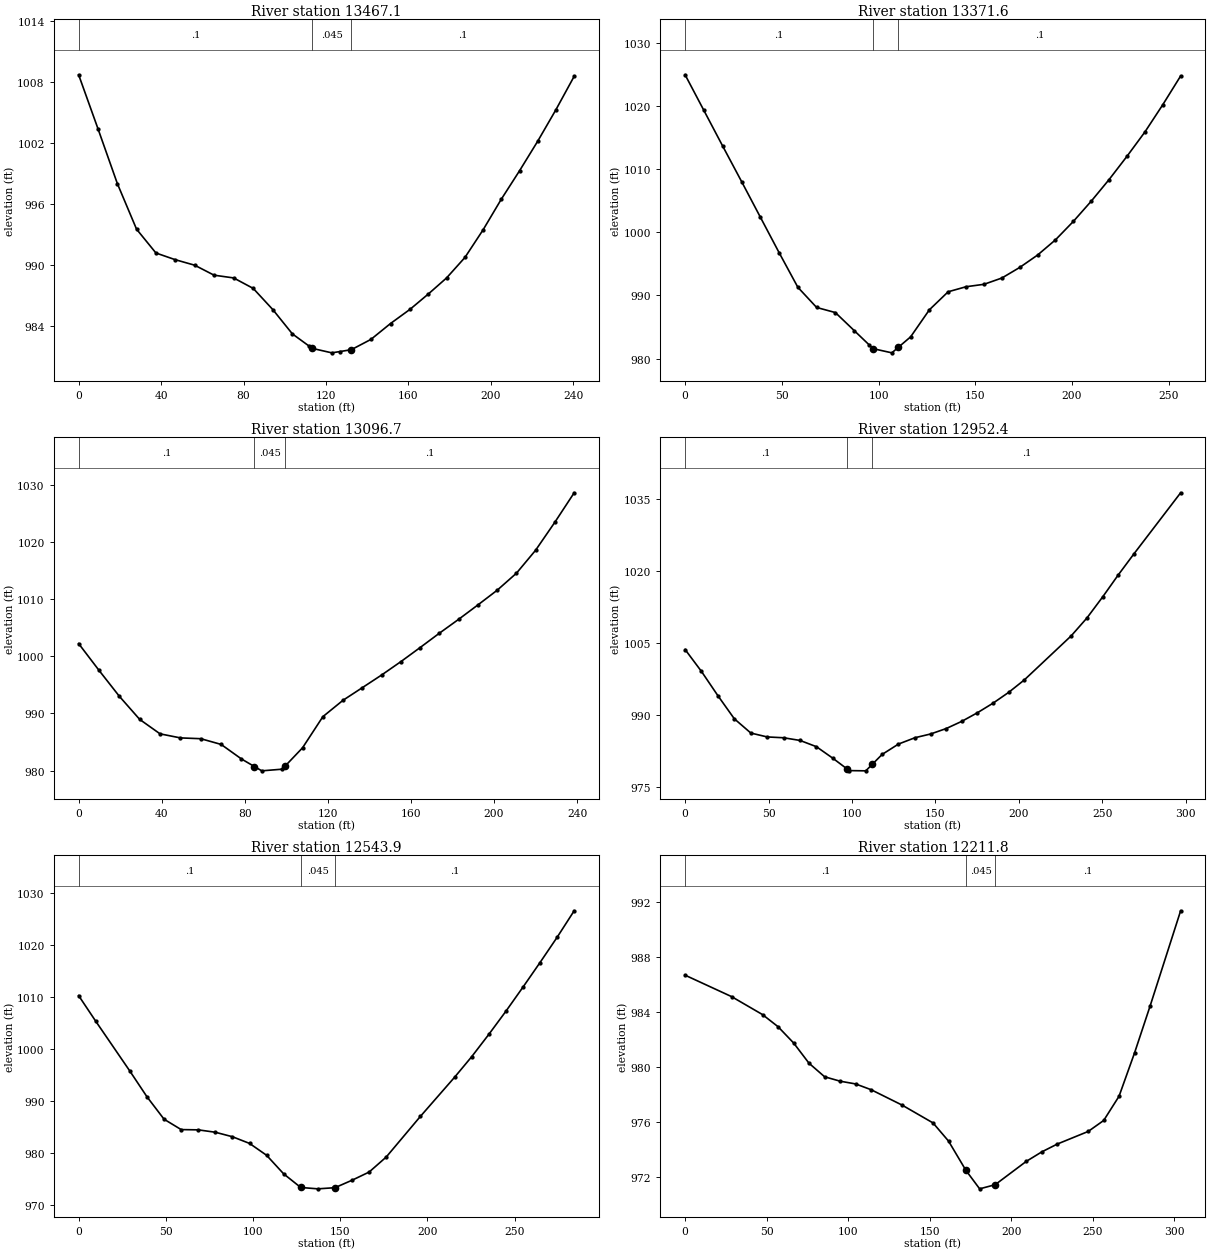
Type RM Length L Ch R = 1 ,13467.1 ,128.5,95.4,65.5
XS GIS Cut Line= 4
     1891220.307      462591.527     1891223.435      462525.936
     1891308.875      462483.979     1891315.446      462404.721
#Sta/Elev= 29
       0 1008.69     9.4 1003.38    18.8  997.99    28.1  993.52    37.5  991.18
    46.9  990.52    56.3  989.98    65.7     989    75.2  988.73    84.7   987.7
    94.2  985.62   103.7  983.23   111.9  982.02   113.3  981.81   122.8  981.37
   126.9   981.5   132.3  981.68   141.8  982.69   151.3  984.25   160.8  985.65
   169.7  987.16   178.5  988.73   187.4  990.74   196.2  993.45     205  996.45
   213.9  999.26   222.7 1002.16   231.5 1005.24   240.4 1008.54
#Mann= 3 , 0 , 0
       0      .1       0   113.3    .045       0   132.3      .1       0
Bank Sta=113.3,132.3
XS Rating Curve= 0 ,0
Exp/Cntr=0.3,0.1

Type RM Length L Ch R = 1 ,13371.6 ,267.4,275,282.3
XS GIS Cut Line= 3
     1891376.468      462618.417     1891357.718      462483.695
     1891357.023      462363.556
#Sta/Elev= 30
       0  1024.9     9.7 1019.27    19.4 1013.64    29.2 1008.01    38.9 1002.38
    48.6  996.76    58.3  991.28      68  988.09    77.7  987.28    87.4  984.44
    95.3  982.13    97.2  981.57   106.9  980.91   110.3   981.8   116.6  983.44
   126.3  987.72     136  990.57   145.3  991.37   154.5  991.75   163.8  992.75
     173  994.42   182.2  996.37   191.5  998.79   200.7 1001.69     210 1004.91
   219.2 1008.32   228.4 1011.98   237.7 1015.84   246.9 1020.13   256.2 1024.71
#Mann= 3 , 0 , 0
       0      .1       0    97.2    .045       0   110.3      .1       0
Bank Sta=97.2,110.3
XS Rating Curve= 0 ,0
Exp/Cntr=0.3,0.1

Type RM Length L Ch R = 1 ,13096.7 ,143,144.3,144.9
XS GIS Cut Line= 3
      1891611.19       462564.25     1891635.496       462439.25
      1891604.94      462332.306
#Sta/Elev= 28
       0 1002.24     9.8  997.56    19.6  993.01    29.4  988.96    39.2  986.43
      49  985.72    58.8  985.58    68.6  984.58    78.4  982.03    84.6  980.71
    88.2  979.95      98  980.24    99.6  980.85   107.8  983.98   117.6  989.44
   127.3  992.31   136.6  994.52   145.9  996.74   155.2  999.09   164.4 1001.54
   173.7 1004.06     183  1006.5   192.2    1009   201.5 1011.58   210.8 1014.57
     220 1018.58   229.3  1023.5   238.6 1028.66
#Mann= 3 , 0 , 0
       0      .1       0    84.6    .045       0    99.6      .1       0
Bank Sta=84.6,99.6
XS Rating Curve= 0 ,0
Exp/Cntr=0.3,0.1

Type RM Length L Ch R = 1 ,12952.4 ,386.1,408.5,429.3
XS GIS Cut Line= 3
     1891745.218      462603.139     1891777.162      462469.111
     1891885.496      462352.445
#Sta/Elev= 30
       0  1003.7     9.8  999.14    19.7  994.06    29.5  989.27    39.4   986.3
    49.2  985.49      59  985.32    68.9  984.76    78.7  983.46    88.6  981.04
    97.1  978.82    98.4  978.48   108.3  978.43   112.1  979.76   118.1  981.85
   127.9  984.01   137.8  985.33   147.2  986.11   156.5  987.24   165.9  988.75
   175.2  990.53   184.6  992.53     194  994.79   203.3  997.36   231.4 1006.54
   240.8 1010.25   250.2 1014.62   259.5 1019.18   268.9 1023.57     297 1036.34
#Mann= 3 , 0 , 0
       0      .1       0    97.1    .045       0   112.1      .1       0
Bank Sta=97.1,112.1
XS Rating Curve= 0 ,0
Exp/Cntr=0.3,0.1

Type RM Length L Ch R = 1 ,12543.9 ,346.5,332.1,317.2
XS GIS Cut Line= 2
     1891845.493      462839.116     1892108.003      462730.238
#Sta/Elev= 27
       0 1010.24     9.8 1005.33    29.4  995.75    39.2  990.82      49  986.52
    58.8  984.53    68.6  984.48    78.4  984.02    88.2  983.16      98  981.88
   107.8   979.6   117.6  976.03   127.4  973.42   137.2  973.16     147  973.38
   156.8  974.81   166.6  976.38   176.4  979.26     196  987.06   215.6  994.57
   225.4  998.51   235.2 1002.78     245 1007.22   254.8 1011.85   264.6 1016.58
   274.4 1021.42   284.2 1026.52
#Mann= 3 , 0 , 0
       0      .1       0   127.4    .045       0     147      .1       0
Bank Sta=127.4,147
XS Rating Curve= 0 ,0
Exp/Cntr=0.3,0.1

Type RM Length L Ch R = 1 ,12211.8 ,100,78.5,56.2
XS GIS Cut Line= 4
     1891958.554      463193.917     1892085.116      463109.542
     1892128.915      463035.806     1892155.429      462975.167
#Sta/Elev= 25
       0  986.68    28.5  985.12    47.5  983.81      57  982.93    66.6  981.74
      76  980.27    85.6  979.28    95.1  978.96   104.6  978.76   114.1  978.34
   133.1  977.22   152.1  975.92   161.6   974.6   172.3  972.46   180.7  971.12
   190.2  971.42   209.3  973.12   218.8  973.81   228.3  974.38   247.3   975.3
   256.8   976.1   266.2  977.86   275.7  981.01   285.2  984.41     304  991.37
#Mann= 3 , 0 , 0
       0      .1       0   172.3    .045       0   190.2      .1       0
Bank Sta=172.3,190.2
XS Rating Curve= 0 ,0
Exp/Cntr=0.3,0.1

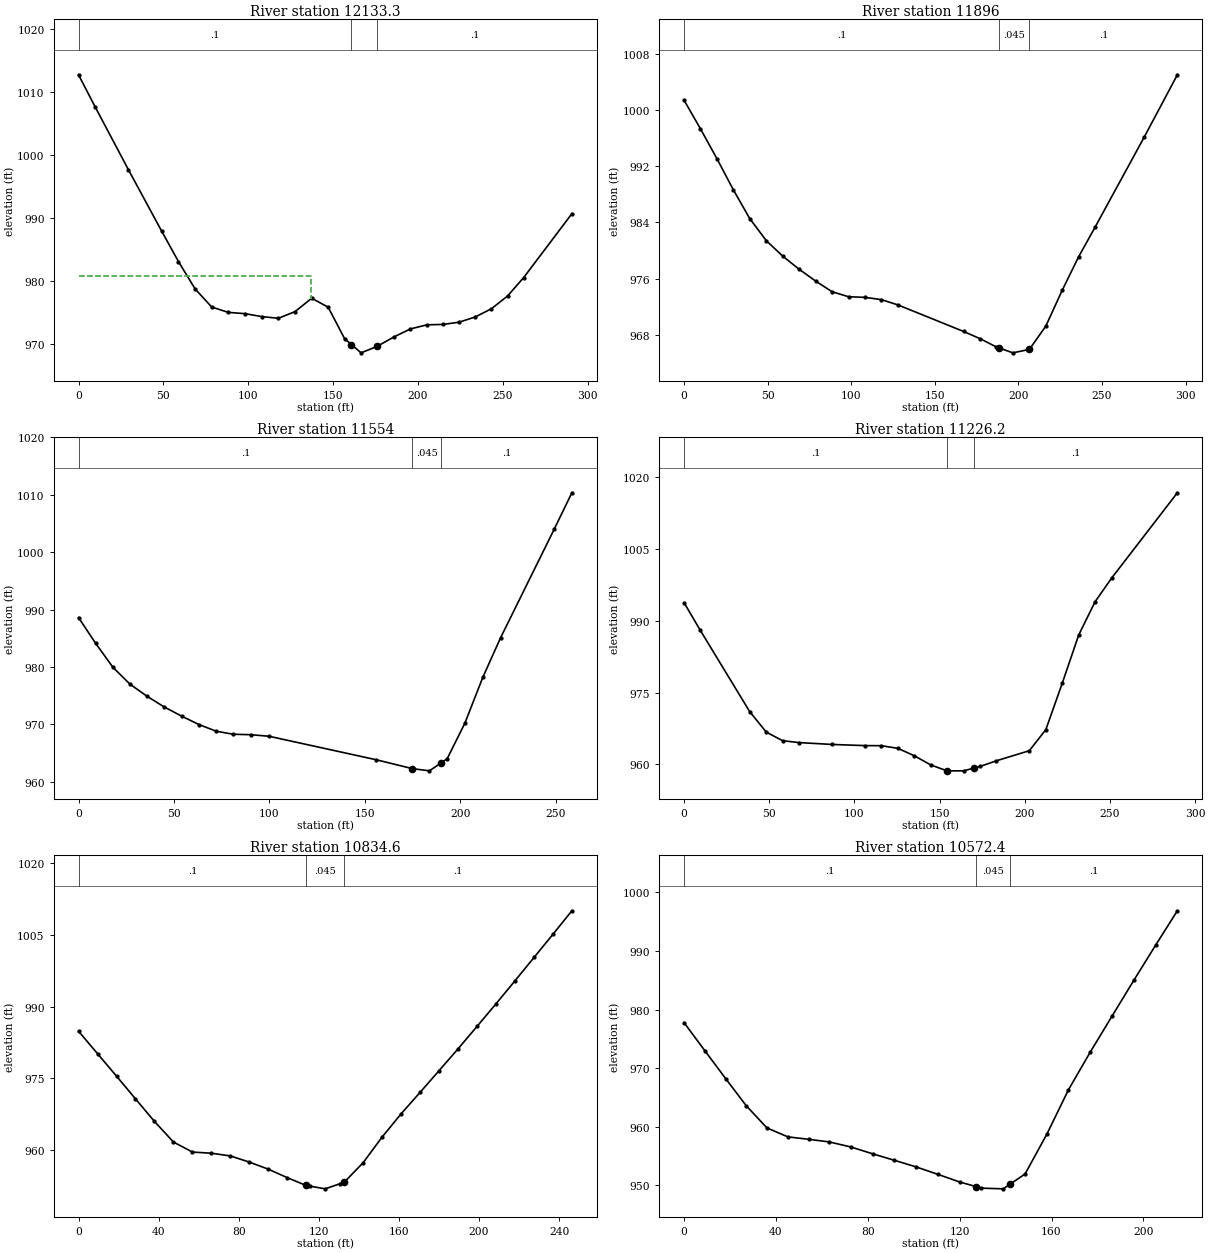
Type RM Length L Ch R = 1 ,12133.3 ,239.1,237.3,235.4
XS GIS Cut Line= 4
     1892196.138      463263.564     1892181.602      463126.926
     1892155.141      463064.363      1892159.59      462979.075
#Sta/Elev= 28
       0 1012.68     9.8 1007.58    29.4  997.61    49.1   987.8    58.9  983.02
    68.7  978.68    78.5   975.8    88.3  974.95    98.2  974.75     108  974.28
   117.8  974.02   127.6  975.08   137.4   977.2   147.1  975.78   156.8  970.77
   160.8  969.85   166.5  968.53   175.8  969.54   185.9  971.06   195.6  972.33
   205.3  972.98   214.8  973.04   224.3   973.4   233.8  974.23   243.3  975.53
   252.8  977.55   262.3  980.48   290.7  990.62
#Mann= 3 , 0 , 0
       0      .1       0   160.8    .045       0   175.8      .1       0
#XS Ineff= 2 , 0
          137.04   980.7
Permanent Ineff=
       F       F
Bank Sta=160.8,175.8
XS Rating Curve= 0 ,0
Exp/Cntr=0.3,0.1

Type RM Length L Ch R = 1 ,11896   ,335.3,342,348.4
XS GIS Cut Line= 2
     1892471.916      463167.579     1892335.153       462906.12
#Sta/Elev= 26
       0 1001.43     9.8  997.36    19.7  993.08    29.5  988.65    39.3  984.55
    49.2   981.4      59   979.2    68.8  977.33    78.7  975.64    88.5  974.12
    98.4   973.4   108.2  973.31     118  972.99   127.9  972.24   167.2  968.45
     177  967.43   186.9  966.23   188.7  966.08   196.7   965.4   206.6  965.89
   216.4  969.21   226.2  974.31     236  979.08   245.9  983.33   275.4  996.22
   295.1 1005.05
#Mann= 3 , 0 , 0
       0      .1       0   188.7    .045       0   206.6      .1       0
Bank Sta=188.7,206.6
XS Rating Curve= 0 ,0
Exp/Cntr=0.3,0.1

Type RM Length L Ch R = 1 ,11554   ,324.3,327.8,331
XS GIS Cut Line= 3
     1892744.647      463068.189     1892724.217      462989.717
     1892690.275       462815.65
#Sta/Elev= 22
       0  988.62       9  984.12      18  979.97      27  977.01      36  974.89
      45  973.03    54.1  971.44    63.1  969.99    72.1  968.83    81.1   968.3
    90.4  968.22    99.8  967.95   155.8  963.87   174.9  962.31   183.8  961.93
   189.9  963.31   193.1  964.04   202.4  970.26   211.8  978.25   221.1  985.13
   249.1 1003.97   258.4 1010.35
#Mann= 3 , 0 , 0
       0      .1       0   174.9    .045       0   189.9      .1       0
Bank Sta=174.9,189.9
XS Rating Curve= 0 ,0
Exp/Cntr=0.3,0.1

Type RM Length L Ch R = 1 ,11226.2 ,390.9,391.5,391.1
XS GIS Cut Line= 2
     1893037.773      463051.168     1893024.932      462761.877
#Sta/Elev= 24
       0  993.81     9.6  987.99    38.6  970.98    48.3  966.72    57.9  964.92
    67.6  964.53    86.9  964.14   106.2   963.9   115.8  963.88   125.5  963.33
   135.1  961.79   144.8  959.86   154.4  958.62   164.1  958.62     170  959.18
   173.8  959.54   183.4  960.73   202.7  962.83   212.4  967.25     222  976.92
   231.7  987.05   241.3     994     251  998.94   289.6 1016.79
#Mann= 3 , 0 , 0
       0      .1       0   154.4    .045       0     170      .1       0
Bank Sta=154.4,170
XS Rating Curve= 0 ,0
Exp/Cntr=0.3,0.1

Type RM Length L Ch R = 1 ,10834.6 ,244.8,262.2,279.6
XS GIS Cut Line= 2
      1893422.99      462961.284      1893413.17      462715.047
#Sta/Elev= 29
       0  984.86     9.5  980.16      19  975.47    28.4  970.77    37.9  966.05
    47.4  961.74    56.9  959.64    66.4   959.4    75.8  958.84    85.3  957.55
    94.8  956.07   104.3  954.29   113.7  952.67   115.8  952.52   123.2  951.97
   130.8  953.07   132.7  953.34   142.2  957.45   151.6  962.76   161.1  967.61
   170.6   972.1   180.1  976.64   189.6   981.2     199  985.84   208.5  990.57
     218  995.38   227.5 1000.24     237  1005.1   246.4 1009.98
#Mann= 3 , 0 , 0
       0      .1       0   113.7    .045       0   132.7      .1       0
Bank Sta=113.7,132.7
XS Rating Curve= 0 ,0
Exp/Cntr=0.3,0.1

Type RM Length L Ch R = 1 ,10572.4 ,307.7,295.6,283.7
XS GIS Cut Line= 3
     1893575.771      462985.399     1893605.653      462929.675
     1893706.199      462816.265
#Sta/Elev= 26
       0  977.78       9  973.01    18.1  968.23    27.1  963.58    36.1   959.8
    45.2  958.27    54.2  957.86    63.2  957.41    72.7  956.54    82.2  955.37
    91.6  954.27   101.1  953.14   110.6  951.86   120.1  950.56   127.1  949.79
   129.5  949.52     139   949.4   142.1  950.23   148.5  951.94     158  958.75
   167.4  966.32   176.9  972.76   186.4  978.91   195.8  984.96   205.3  990.97
   214.8  996.86
#Mann= 3 , 0 , 0
       0      .1       0   127.1    .045       0   142.1      .1       0
Bank Sta=127.1,142.1
XS Rating Curve= 0 ,0
Exp/Cntr=0.3,0.1

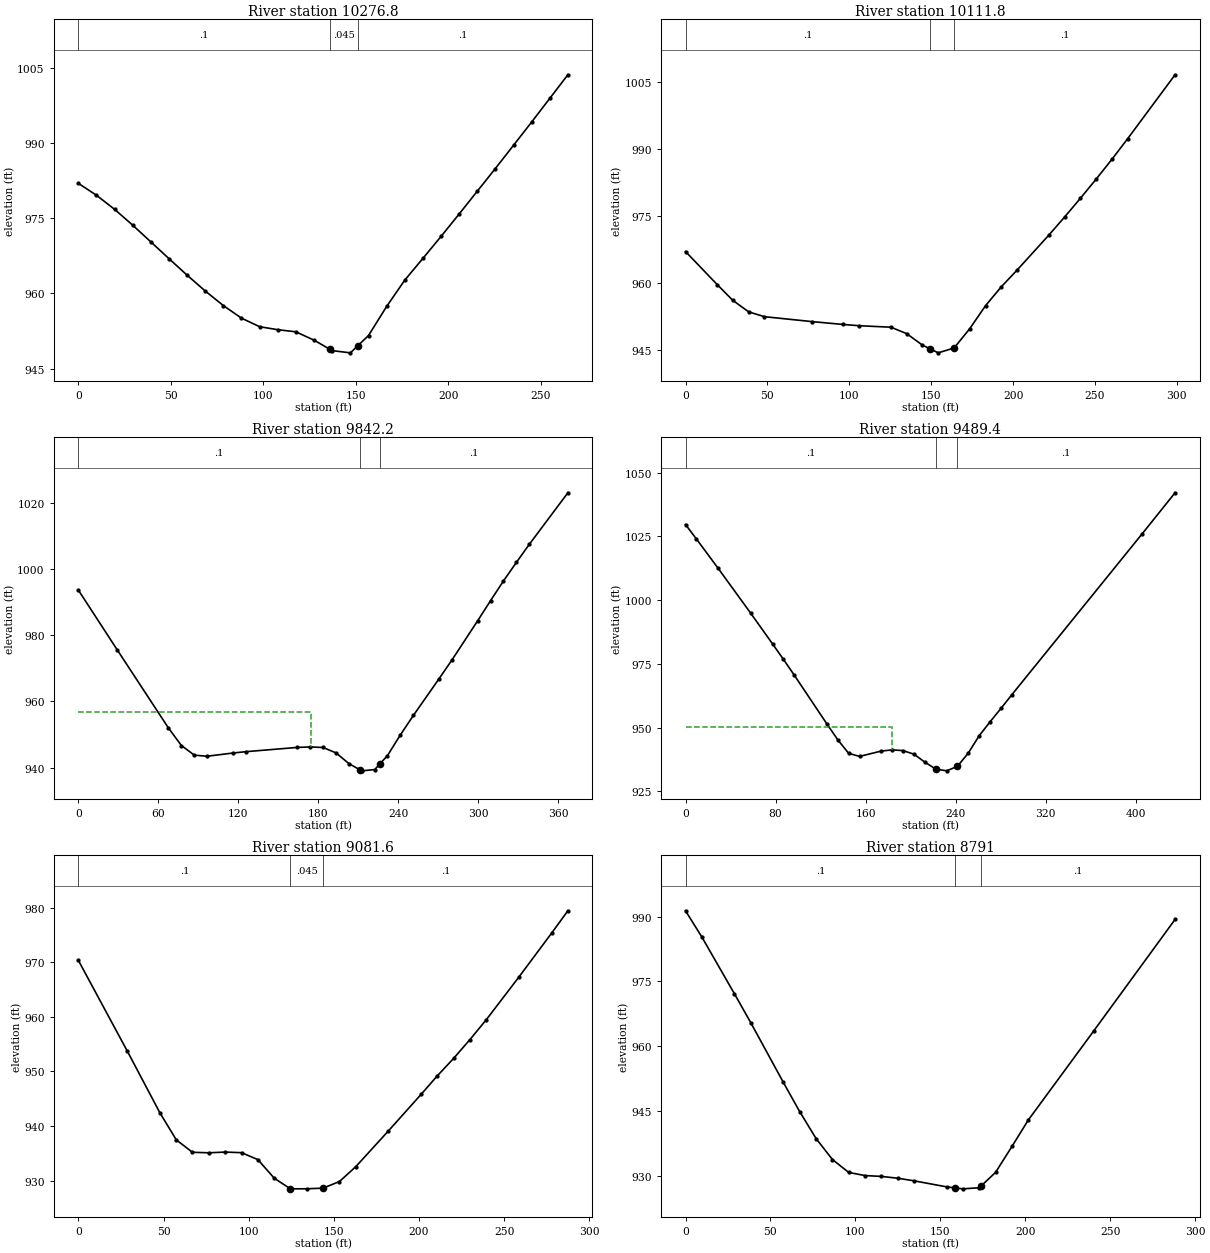
Type RM Length L Ch R = 1 ,10276.8 ,176.8,165,152.8
XS GIS Cut Line= 2
     1893886.761      463144.828     1893937.368      462884.996
#Sta/Elev= 30
       0  981.99     9.8  979.61    19.6   976.8    29.4  973.64    39.2   970.3
      49  966.96    58.8  963.66    68.6   960.5    78.4  957.59    88.2  955.08
      98  953.37   107.8  952.77   117.6  952.35   127.5  950.67   136.1  948.84
   137.3  948.59   147.1  948.15   151.1  949.56   156.9   951.6   166.7  957.41
   176.5  962.66   186.3     967   196.1  971.38   205.9  975.86   215.7  980.41
   225.5  984.95   235.3  989.58   245.1  994.22   254.9  998.94   264.7 1003.66
#Mann= 3 , 0 , 0
       0      .1       0   136.1    .045       0   151.1      .1       0
Bank Sta=136.1,151.1
XS Rating Curve= 0 ,0
Exp/Cntr=0.3,0.1

Type RM Length L Ch R = 1 ,10111.8 ,284.3,269.6,254.5
XS GIS Cut Line= 2
     1894128.666      463142.636      1894029.36      462860.691
#Sta/Elev= 25
       0  967.02    19.3  959.61    28.9  956.04    38.6  953.46    48.2  952.38
    77.1  951.28    96.4  950.63   106.1  950.35   125.4  950.02     135  948.58
   144.6  946.01     149  945.22   154.3  944.26     164  945.35   173.6  949.71
   183.2  954.86   192.8  959.09   202.5  962.87   221.8  970.69   231.4  974.74
   241.1  978.97   250.7  983.27   260.4  987.75     270  992.38   298.9 1006.72
#Mann= 3 , 0 , 0
       0      .1       0     149    .045       0     164      .1       0
Bank Sta=149,164
XS Rating Curve= 0 ,0
Exp/Cntr=0.3,0.1

Type RM Length L Ch R = 1 ,9842.2  ,354.4,352.8,351.1
XS GIS Cut Line= 2
     1894448.742       462927.62     1894140.187      462728.484
#Sta/Elev= 28
       0  993.66      29  975.69    67.6  951.96    77.3  946.67      87  943.76
    96.6  943.42     116   944.4   125.6   944.8   164.3  946.09     174  946.24
   183.6  946.07   193.3  944.43     203  941.19   211.2  939.33   212.6  939.01
   222.3  939.39   226.2  941.11   231.9  943.63   241.6   949.9   251.3  955.75
   270.6  966.87   280.3  972.56   299.6  984.42   309.2  990.46   318.9  996.43
   328.6 1002.03   338.2 1007.45   367.2 1023.07
#Mann= 3 , 0 , 0
       0      .1       0   211.2    .045       0   226.2      .1       0
#XS Ineff= 2 , 0
           174.5   956.8
Permanent Ineff=
       F       F
Bank Sta=211.2,226.2
XS Rating Curve= 0 ,0
Exp/Cntr=0.3,0.1

Type RM Length L Ch R = 1 ,9489.4  ,402.8,407.8,412.5
XS GIS Cut Line= 2
     1894644.683      462615.183     1894262.996      462407.037
#Sta/Elev= 26
       0 1029.67     9.7 1023.99      29 1012.48      58  994.82    77.3  982.85
      87  976.75    96.6  970.58   125.6  951.43   135.3  945.18   144.9  939.91
   154.6   938.7   173.9   940.8   183.6  941.26   193.2  940.98   202.9  939.57
   212.6  936.45   222.2  933.75   231.9  933.04   241.5  934.79   251.2  940.05
   260.8  946.79   270.5  952.27   280.2  957.53   289.8  962.88   405.8 1026.14
   434.8 1042.12
#Mann= 3 , 0 , 0
       0      .1       0   222.2    .045       0   241.5      .1       0
#XS Ineff= 2 , 0
          183.78   950.1
Permanent Ineff=
       F       F
Bank Sta=222.2,241.5
XS Rating Curve= 0 ,0
Exp/Cntr=0.3,0.1

Type RM Length L Ch R = 1 ,9081.6  ,283.7,290.6,297.4
XS GIS Cut Line= 2
      1894765.04      462253.948     1894548.026      462065.579
#Sta/Elev= 24
       0  970.33    28.7  953.74    47.9  942.41    57.5  937.47      67  935.19
    76.6   935.1    86.2  935.23    95.8  935.12   105.4  933.85     115  930.45
   124.5   928.5   134.1  928.51   143.7  928.63   153.3  929.84   162.8  932.53
     182  939.09   201.2  945.78   210.7  949.17   220.3  952.37   229.9  955.82
   239.5  959.46   258.6  967.25   277.8  975.29   287.4   979.4
#Mann= 3 , 0 , 0
       0      .1       0   124.5    .045       0   143.7      .1       0
Bank Sta=124.5,143.7
XS Rating Curve= 0 ,0
Exp/Cntr=0.3,0.1

Type RM Length L Ch R = 1 ,8791    ,343.4,346.8,350.1
XS GIS Cut Line= 2
     1894949.797      462098.774     1894798.547      461853.427
#Sta/Elev= 23
       0  991.36     9.6   985.3    28.8  972.14    38.4  965.45    57.6  951.61
    67.2  944.85    76.9  938.58    86.5  933.74    96.1  930.75   105.7  930.02
   115.3  929.83   124.9  929.41   134.5  928.81   153.7  927.41   158.8  927.17
   163.3  926.95   172.9   927.2   173.8  927.53   182.5  930.75   192.2  936.78
   201.8  942.89   240.2  963.46   288.2  989.35
#Mann= 3 , 0 , 0
       0      .1       0   158.8    .045       0   173.8      .1       0
Bank Sta=158.8,173.8
XS Rating Curve= 0 ,0
Exp/Cntr=0.3,0.1

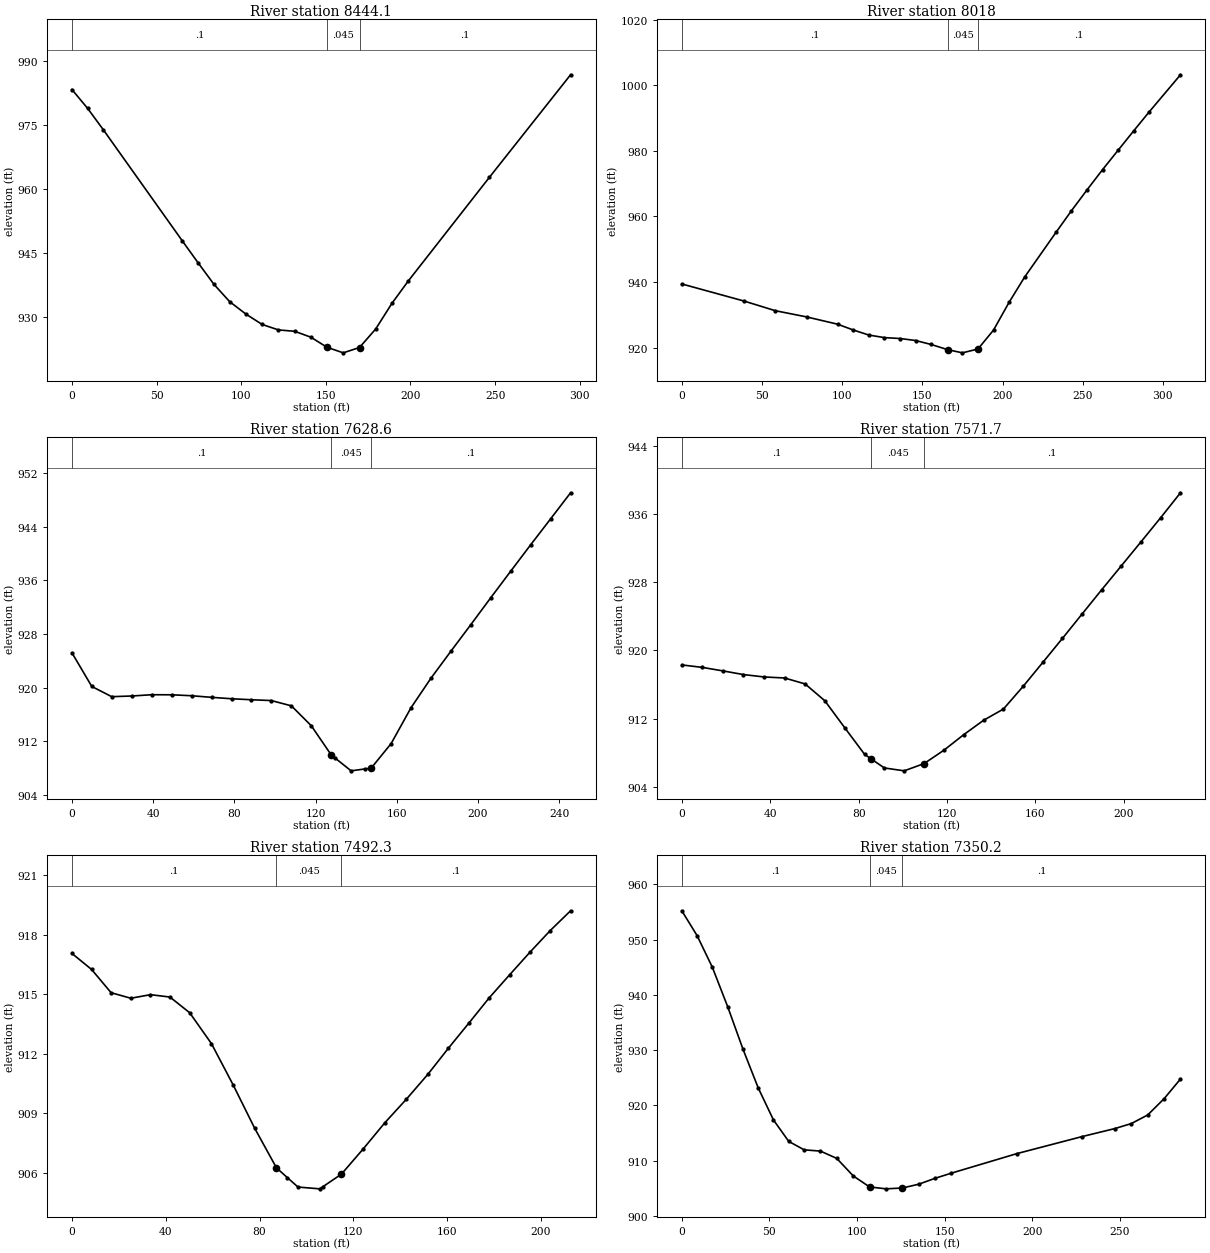
Type RM Length L Ch R = 1 ,8444.1  ,418.1,426.1,434
XS GIS Cut Line= 3
     1895212.957      461981.378     1895209.788      461888.236
     1895130.734         461703.
#Sta/Elev= 20
       0  983.26     9.3  978.83    18.6   973.8    65.2   947.8    74.6  942.62
    83.9  937.61    93.2  933.54   102.8  930.63   112.4   928.2     122  926.92
   131.6   926.6   141.2  925.21   150.7  922.85   160.3  921.55   169.9   922.8
   179.5  927.16   189.1  933.17   198.7  938.38   246.6  962.66   294.6  986.71
#Mann= 3 , 0 , 0
       0      .1       0   150.7    .045       0   169.9      .1       0
Bank Sta=150.7,169.9
XS Rating Curve= 0 ,0
Exp/Cntr=0.3,0.1

Type RM Length L Ch R = 1 ,8018    ,394,389.5,384.7
XS GIS Cut Line= 2
     1895605.454      461972.537     1895589.788      461661.906
#Sta/Elev= 25
       0  939.39    38.9  934.17    58.3  931.24    77.8  929.35    97.2  927.12
   106.9  925.36   116.6  923.82   126.4  923.03   136.1  922.76   145.8  922.15
   155.5  920.94   165.8  919.36     175  918.39   184.7  919.56   194.4  925.33
   204.1  933.79   213.8   941.5   233.3  955.09     243  961.72   252.7  968.07
   262.4  974.25   272.2  980.23   281.9  986.13   291.6  991.93     311 1003.18
#Mann= 3 , 0 , 0
       0      .1       0   165.8    .045       0   184.7      .1       0
Bank Sta=165.8,184.7
XS Rating Curve= 0 ,0
Exp/Cntr=0.3,0.1

Type RM Length L Ch R = 1 ,7628.6  ,42.1,56.8,72.1
XS GIS Cut Line= 2
     1896007.864      461833.975     1895945.364      461596.475
#Sta/Elev= 28
       0  925.19     9.8  920.16    19.6  918.64    29.5  918.74    39.3  918.93
    49.1  918.92    58.9  918.78    68.8  918.54    78.6  918.33    88.4  918.18
    98.2  918.06   108.1  917.27   117.9   914.3   127.7  909.95   129.5  909.51
   137.5  907.57   144.5  907.86   147.4  907.98   157.2  911.63     167  916.98
   176.8  921.38   186.6   925.4   196.5   929.4   206.3  933.41   216.1  937.36
   225.9  941.29   235.8  945.19   245.6  949.07
#Mann= 3 , 0 , 0
       0      .1       0   127.7    .045       0   147.4      .1       0
Bank Sta=127.7,147.4
XS Rating Curve= 0 ,0
Exp/Cntr=0.3,0.1

Type RM Length L Ch R = 1 ,7571.7  ,78.9,79.4,77.5
XS GIS Cut Line= 4
     1896030.104      461772.212     1896015.897      461718.297
     1896041.506      461632.314      1896023.16       461554.33
#Sta/Elev= 27
       0   918.3     9.3  918.01    18.6   917.6    27.9  917.17    37.2  916.89
    46.5  916.77    55.8  916.07    64.7   914.1    73.7  910.94    82.7  907.82
    85.6   907.3    91.6  906.23   100.6  905.89   109.6  906.74   118.6  908.31
   127.5  910.12   136.5  911.81   145.5  913.13   154.4  915.78   163.3  918.59
   172.2  921.41   181.1  924.27     190  927.12   198.9  929.93   207.8  932.74
   216.7  935.57   225.6  938.47
#Mann= 3 , 0 , 0
       0      .1       0    85.6    .045       0   109.6      .1       0
Bank Sta=85.6,109.6
XS Rating Curve= 0 ,0
Exp/Cntr=0.3,0.1

Type RM Length L Ch R = 1 ,7492.3  ,142.7,142.1,142.6
XS GIS Cut Line= 4
     1896096.511      461747.906     1896085.679      461698.867
     1896114.681      461601.492      1896119.08      461540.875
#Sta/Elev= 27
       0  917.05     8.4  916.24    16.7  915.07    25.1  914.79    33.5  914.97
    41.8  914.85    50.2  914.06    59.5   912.5    68.7  910.43    77.9  908.24
    87.2  906.24    91.9  905.74    96.4  905.27   105.6  905.18   106.9  905.28
   114.9  905.92   124.1  907.18   133.4  908.51   142.6   909.7   151.8  910.96
   160.5  912.27   169.2  913.53   177.9  914.81   186.6  915.97   195.2   917.1
   203.9   918.2   212.6   919.2
#Mann= 3 , 0 , 0
       0      .1       0    87.2    .045       0   114.9      .1       0
Bank Sta=87.2,114.9
XS Rating Curve= 0 ,0
Exp/Cntr=0.3,0.1

Type RM Length L Ch R = 1 ,7350.2  ,255,266.6,277.7
XS GIS Cut Line= 4
     1896213.752      461779.727     1896217.976      461710.107
     1896262.334      461597.018     1896311.617      461517.826
#Sta/Elev= 25
       0  955.23     8.7  950.74    17.4  945.02    26.2  937.84    34.9  930.18
    43.6  923.16    52.3  917.36      61  913.49    69.8  911.96    79.1  911.73
    88.4  910.41    97.8  907.24   107.1  905.25   116.5   904.9   125.8  905.05
   135.2  905.74   144.5  906.81   153.8  907.74   191.2  911.28   228.5  914.37
   247.2  915.82   256.5  916.72   265.8  918.27   275.2  921.23   284.5  924.78
#Mann= 3 , 0 , 0
       0      .1       0   107.1    .045       0   125.8      .1       0
Bank Sta=107.1,125.8
XS Rating Curve= 0 ,0
Exp/Cntr=0.3,0.1

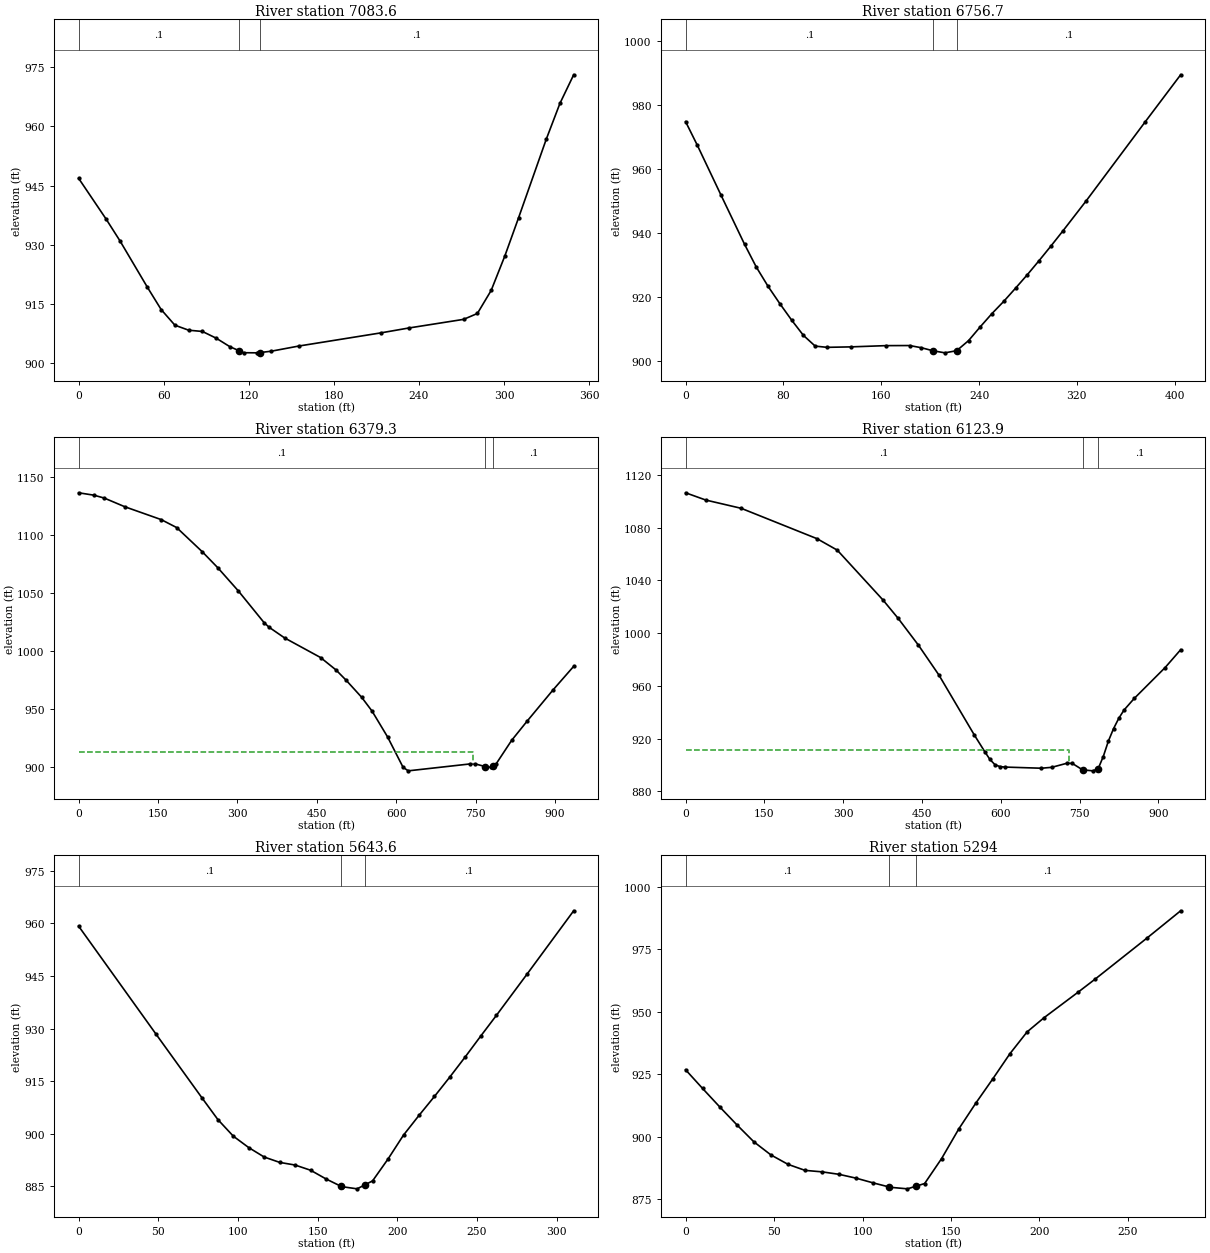
Type RM Length L Ch R = 1 ,7083.6  ,330.4,326.9,323.3
XS GIS Cut Line= 2
     1896357.761      461886.796     1896625.378      461662.628
#Sta/Elev= 26
       0  946.83    19.4  936.49    29.1  931.01    48.5  919.21    58.2  913.56
    67.9  909.59    77.6  908.32    87.3     908      97   906.3   106.7  904.13
   113.1  903.13   116.4  902.61   126.1  902.58   128.1  902.66   135.8  902.99
   155.2   904.3   213.3  907.65   232.7  908.87   271.5  911.07   281.2  912.56
   290.9  918.39   300.6  927.18   310.3  936.88   329.7  956.68   339.4  965.82
   349.1  973.08
#Mann= 3 , 0 , 0
       0      .1       0   113.1    .045       0   128.1      .1       0
Bank Sta=113.1,128.1
XS Rating Curve= 0 ,0
Exp/Cntr=0.3,0.1

Type RM Length L Ch R = 1 ,6756.7  ,390.7,377.4,364.1
XS GIS Cut Line= 2
     1896563.937        462176.3     1896829.239       461870.44
#Sta/Elev= 30
       0  974.73     9.6  967.35    28.9  951.82    48.2  936.43    57.8  929.31
    67.5  923.24    77.1  917.85    86.8  912.68    96.4  907.93     106  904.59
   115.7  904.21     135  904.35   163.9  904.74   183.2  904.77   192.8  904.09
   202.4  903.13   212.1  902.49   221.7  903.16   231.4   906.3     241  910.62
   250.6  914.77   260.3  918.61   269.9  922.71   279.6  926.95   289.2  931.34
   298.8  935.86   308.5  940.54   327.8  950.06     376  974.72   404.9  989.37
#Mann= 3 , 0 , 0
       0      .1       0   202.4    .045       0   221.7      .1       0
Bank Sta=202.4,221.7
XS Rating Curve= 0 ,0
Exp/Cntr=0.3,0.1

Type RM Length L Ch R = 1 ,6379.3  ,265,255.4,245.7
XS GIS Cut Line= 4
     1896728.552      462818.286     1896799.732      462647.279
     1897021.955      462390.335     1897073.188      461983.497
#Sta/Elev= 30
       0 1136.42    29.2 1134.32    48.7 1131.82    87.7  1124.3     156 1113.29
   185.2 1106.43   233.8 1085.48   262.9 1071.78   301.7  1051.8   350.2 1024.53
   359.9 1020.45   389.1 1011.28     457  994.39   486.1   983.7   505.5  974.71
   534.7  960.06   554.2  948.22   583.5  925.97   612.8  899.76   622.6  896.72
   739.7  902.69   749.5  902.66   768.3  900.34   778.8  899.77   783.3  901.13
   788.5   902.7   817.8  922.97   847.1  939.59   895.9  966.41     935   986.8
#Mann= 3 , 0 , 0
       0      .1       0   768.3    .045       0   783.3      .1       0
#XS Ineff= 2 , 0
          745.55  913.04
Permanent Ineff=
       F       F
Bank Sta=768.3,783.3
XS Rating Curve= 0 ,0
Exp/Cntr=0.3,0.1

Type RM Length L Ch R = 1 ,6123.9  ,491.2,480.3,468.8
XS GIS Cut Line= 4
     1897578.378      462811.342     1897549.732      462524.016
     1897371.389        462333.5     1897254.233      461958.637
#Sta/Elev= 30
       0 1106.41    38.5 1100.89   105.9 1094.63   250.2 1071.61   288.8 1062.91
   375.7 1025.17   404.7 1011.19   443.4  990.81   482.1  968.34   549.7  922.76
   569.4  910.24   579.2  904.32     589  900.24   598.8  898.78   608.6  898.45
   677.4  897.58     697  898.26   726.4   901.4   736.3  901.21   755.9  896.32
   775.5   895.6   785.4   897.2   795.2  906.47     805  918.28   814.8  927.65
   824.6  935.34   834.5  941.61   854.1  950.49     913  973.93   942.5  987.42
#Mann= 3 , 0 , 0
       0      .1       0   755.9    .045       0   785.4      .1       0
#XS Ineff= 2 , 0
          729.28   911.6
Permanent Ineff=
       F       F
Bank Sta=755.9,785.4
XS Rating Curve= 0 ,0
Exp/Cntr=0.3,0.1

Type RM Length L Ch R = 1 ,5643.6  ,349,349.6,350.3
XS GIS Cut Line= 2
     1897828.516      461982.305     1897605.875      461765.588
#Sta/Elev= 26
       0   959.2    48.6   928.4    77.7  910.07    87.4  904.06    97.1  899.32
   106.8  896.06   116.5  893.37   126.2  891.85   135.9  891.09   145.6  889.61
   155.4   887.1   164.7  885.03   165.1  884.94   174.8  884.31   179.7  885.46
   184.5  886.58   194.2  892.82   203.9  899.63   213.6  905.23   223.3  910.64
     233   916.2   242.7  921.96   252.4  927.88   262.2  933.76   281.6  945.62
   310.7  963.58
#Mann= 3 , 0 , 0
       0      .1       0   164.7    .045       0   179.7      .1       0
Bank Sta=164.7,179.7
XS Rating Curve= 0 ,0
Exp/Cntr=0.3,0.1

Type RM Length L Ch R = 1 ,5294    ,348.8,349.5,350.3
XS GIS Cut Line= 2
      1898026.48      461692.224     1897831.599      461491.437
#Sta/Elev= 28
       0  926.82     9.6  919.36    19.3  911.98      29  904.82    38.6  898.03
    48.2  892.81    57.9  889.03    67.5  886.63    77.2  886.03    86.8  885.04
    96.5  883.49   106.1  881.61     115     880   115.8  879.86   125.4  879.25
     130  880.26   135.1  881.37   144.7  891.35   154.4  903.18     164  913.47
   173.7  923.27   183.3  933.24     193  941.95   202.6  947.63   221.9  957.86
   231.6  963.12   260.5   979.3   279.8  990.35
#Mann= 3 , 0 , 0
       0      .1       0     115    .045       0     130      .1       0
Bank Sta=115,130
XS Rating Curve= 0 ,0
Exp/Cntr=0.3,0.1