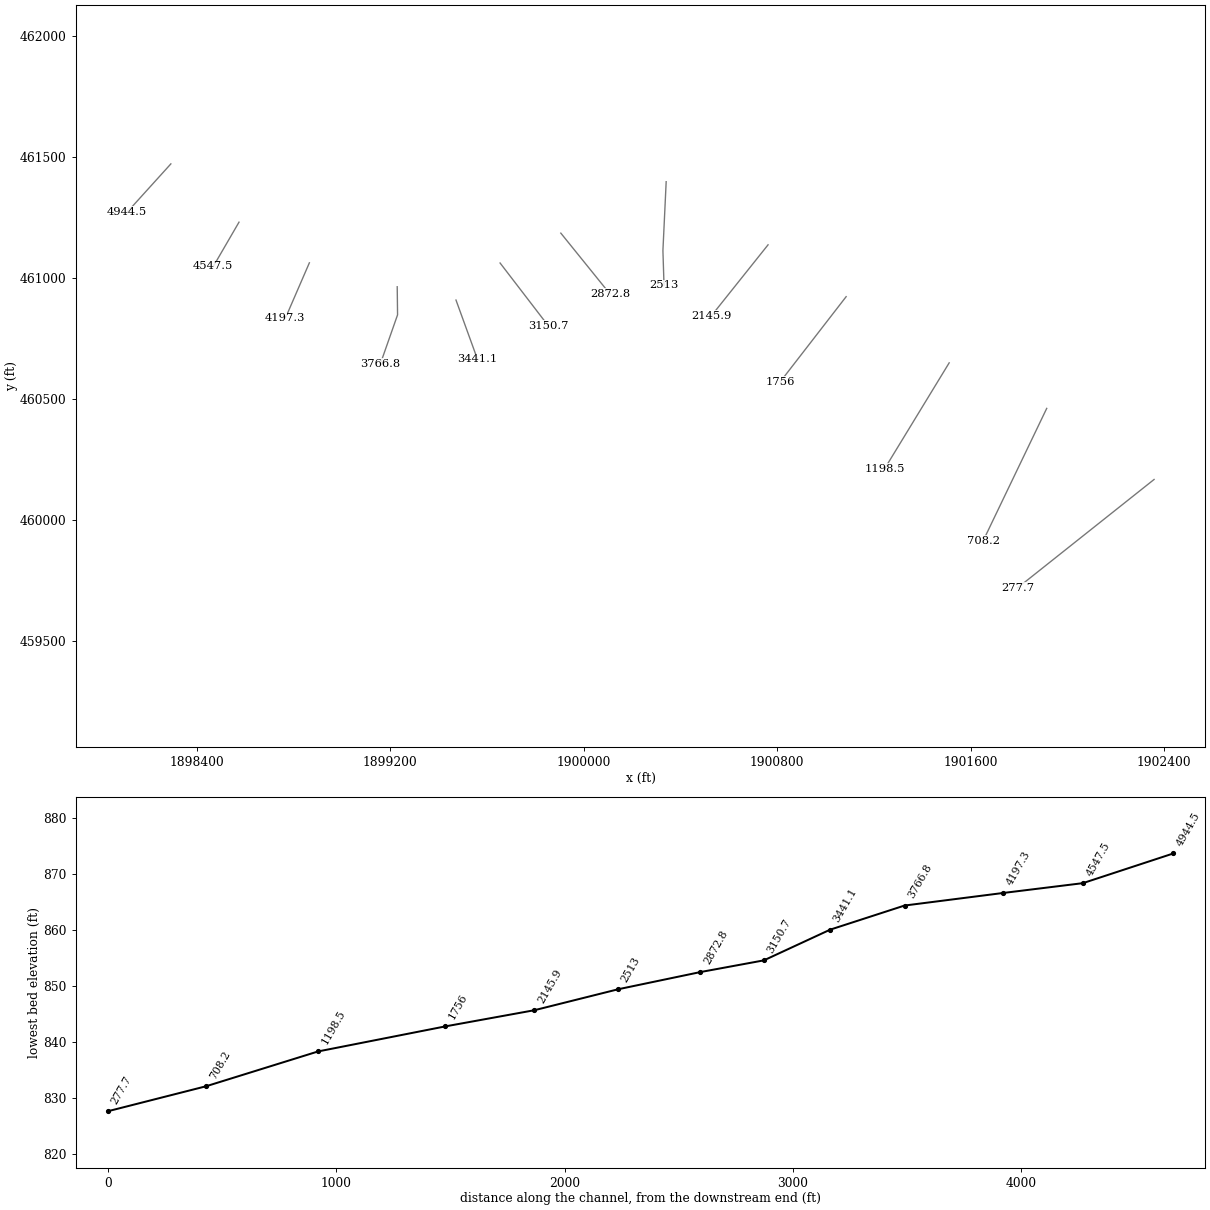
HEC-RAS study BELLSCK.prj: BELLSCK

--- BELLSCK.g01 (geometry) --- (continued)

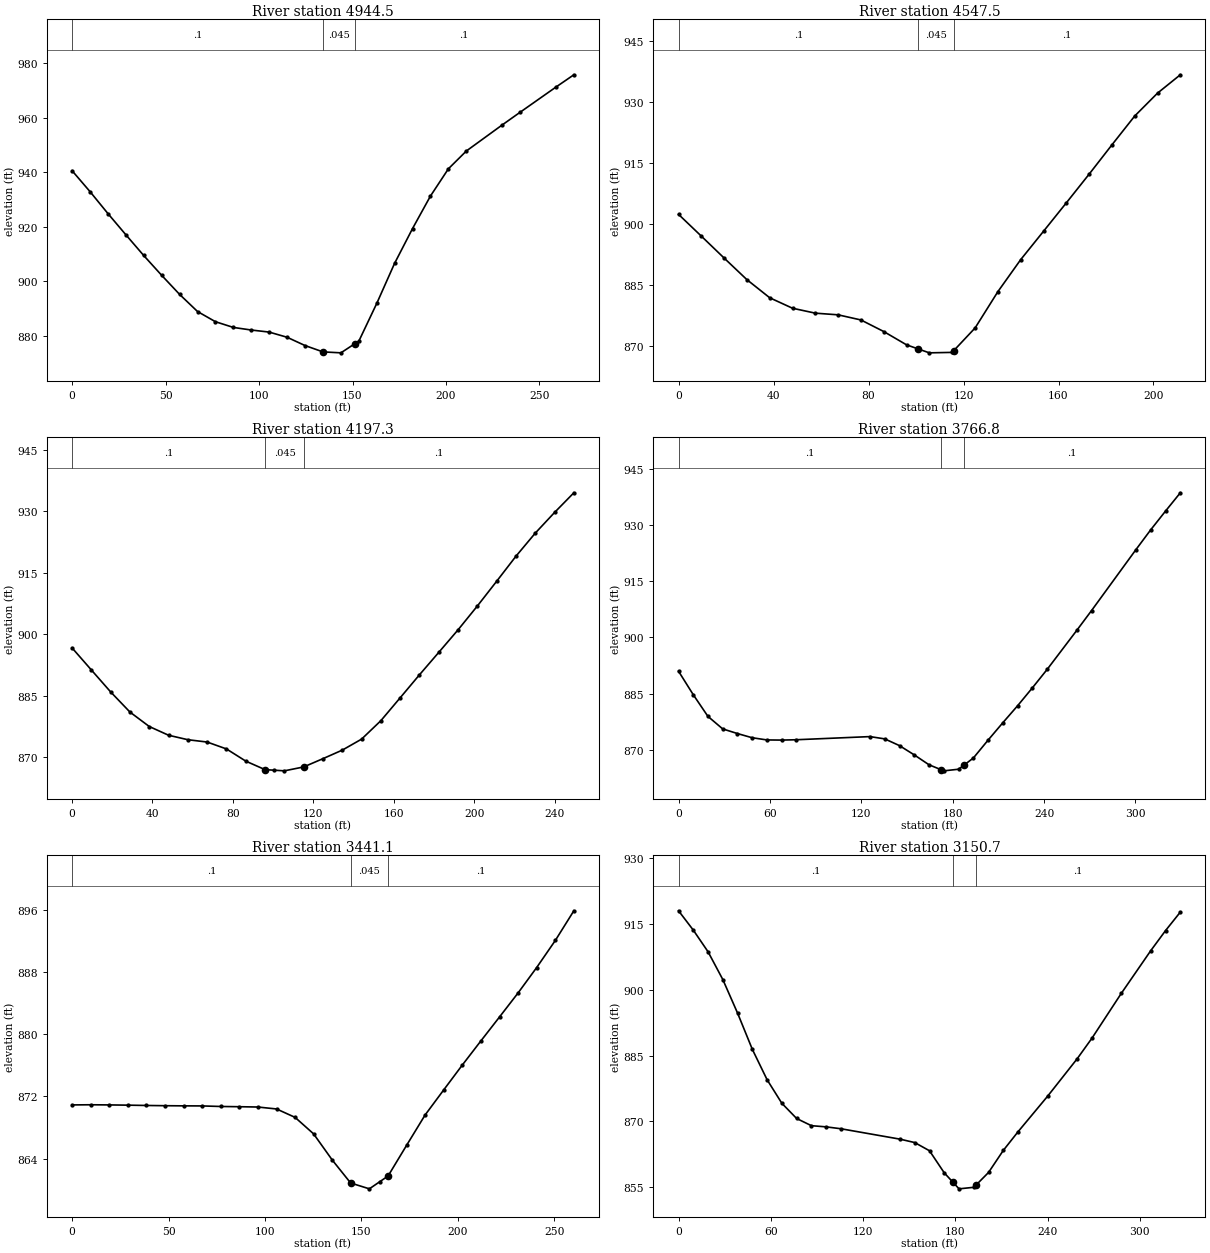
Type RM Length L Ch R = 1 ,4944.5  ,392.2,397,401.7
XS GIS Cut Line= 2
     1898291.907      461471.095     1898111.579      461272.325
#Sta/Elev= 28
       0   940.6     9.6  932.92    19.2  924.85    28.8  917.06    38.3  909.49
    47.9  902.22    57.5  895.21    67.1  888.92    76.7  885.17    86.3  883.07
    95.8  882.13   105.4  881.37     115  879.47   124.6  876.43   134.2   874.1
   143.8  873.75   151.1  877.03   153.4  878.06     163  891.93   172.5  906.58
   182.1  919.35   191.7   931.3   201.3   941.3   210.9  947.83     230  957.35
   239.6  962.02   258.8  971.28   268.4   975.8
#Mann= 3 , 0 , 0
       0      .1       0   134.2    .045       0   151.1      .1       0
Bank Sta=134.2,151.1
XS Rating Curve= 0 ,0
Exp/Cntr=0.3,0.1

Type RM Length L Ch R = 1 ,4547.5  ,347.6,350.2,352.9
XS GIS Cut Line= 2
     1898573.742      461230.569     1898467.492       461047.93
#Sta/Elev= 25
       0  902.46     9.6  897.11    19.2  891.72    28.8  886.41    38.4  881.96
      48  879.39    57.6  878.18    67.2  877.77    76.8  876.51    86.4  873.67
      96   870.4   100.9  869.39   105.6  868.43   115.2  868.54   115.9  868.97
   124.9  874.56   134.5  883.49   144.1  891.35   153.7  898.31   163.3  905.29
   172.9  912.34   182.5  919.54   192.1  926.63   201.7  932.25   211.3  936.76
#Mann= 3 , 0 , 0
       0      .1       0   100.9    .045       0   115.9      .1       0
Bank Sta=100.9,115.9
XS Rating Curve= 0 ,0
Exp/Cntr=0.3,0.1

Type RM Length L Ch R = 1 ,4197.3  ,428.4,430.5,431.6
XS GIS Cut Line= 2
     1898864.762      461062.758      1898765.36      460833.796
#Sta/Elev= 29
       0  896.65     9.6  891.27    19.2  885.91    28.8     881    38.4  877.48
      48  875.35    57.6  874.26    67.2  873.69    76.8  872.01    86.4  869.04
      96  866.96   100.4  866.83   105.6  866.67   115.2  867.62   115.4  867.66
   124.8  869.64   134.4  871.72     144   874.4   153.6   878.9   163.2  884.48
   172.8  890.09   182.4  895.56     192  901.06   201.6  906.87   211.2   912.9
   220.8  919.01   230.4  924.64     240  929.68   249.6  934.48
#Mann= 3 , 0 , 0
       0      .1       0      96    .045       0   115.4      .1       0
Bank Sta=96,115.4
XS Rating Curve= 0 ,0
Exp/Cntr=0.3,0.1

Type RM Length L Ch R = 1 ,3766.8  ,309.9,325.7,340.9
XS GIS Cut Line= 3
     1899228.082      460963.902     1899229.471       460847.93
     1899158.638      460646.541
#Sta/Elev= 30
       0  890.99     9.7  884.71    19.3  878.95      29  875.61    38.7  874.37
    48.3  873.26      58  872.67    67.7  872.63    77.3  872.72   125.7  873.56
   135.4  872.95   145.1  871.15   154.8  868.68   164.5  866.04   172.3  864.75
   174.2  864.43   183.9  864.86   187.3  865.91   193.6  867.85   203.3  872.64
     213  877.28   222.7  881.81   232.4  886.58   242.1   891.5   261.5  901.88
   271.2  907.16   300.4  923.44   310.1  928.72   319.8   933.7   329.5  938.57
#Mann= 3 , 0 , 0
       0      .1       0   172.3    .045       0   187.3      .1       0
Bank Sta=172.3,187.3
XS Rating Curve= 0 ,0
Exp/Cntr=0.3,0.1

Type RM Length L Ch R = 1 ,3441.1  ,283.5,290.4,297.4
XS GIS Cut Line= 2
     1899471.138      460909.041     1899560.027      460664.597
#Sta/Elev= 29
       0   870.9     9.6  870.92    19.3   870.9    28.9  870.87    38.5  870.83
    48.2   870.8    57.8  870.78    67.4  870.77    77.1   870.7    86.7  870.67
    96.3  870.63     106  870.38   115.6   869.3   125.2  867.18   134.9  863.81
   144.4  860.87   154.1  860.12   159.4  861.02   163.8  861.77   173.4  865.71
     183  869.61   192.7  872.85   202.3  876.03   211.9  879.12   221.6  882.21
   231.2  885.29   240.8  888.54   250.5  892.03   260.1  895.84
#Mann= 3 , 0 , 0
       0      .1       0   144.4    .045       0   163.8      .1       0
Bank Sta=144.4,163.8
XS Rating Curve= 0 ,0
Exp/Cntr=0.3,0.1

Type RM Length L Ch R = 1 ,3150.7  ,277.3,277.8,278.5
XS GIS Cut Line= 2
     1899653.485      461062.006     1899852.409      460803.312
#Sta/Elev= 30
       0  918.03     9.6  913.62    19.2  908.68    28.8  902.35    38.4  894.69
      48  886.43    57.6   879.5    67.2  874.13    76.8  870.67    86.4  869.03
      96  868.76   105.6  868.33     144  865.96   153.6  865.18   163.2  863.31
   172.8  858.27   178.4  856.15   182.4  854.63     192  854.98   193.4  855.47
   201.6  858.37   211.2   863.4   220.8  867.66     240  875.75   259.2  884.28
   268.8  888.96   287.9  899.19   307.1  908.95   316.7  913.52   326.3  917.73
#Mann= 3 , 0 , 0
       0      .1       0   178.4    .045       0   193.4      .1       0
Bank Sta=178.4,193.4
XS Rating Curve= 0 ,0
Exp/Cntr=0.3,0.1

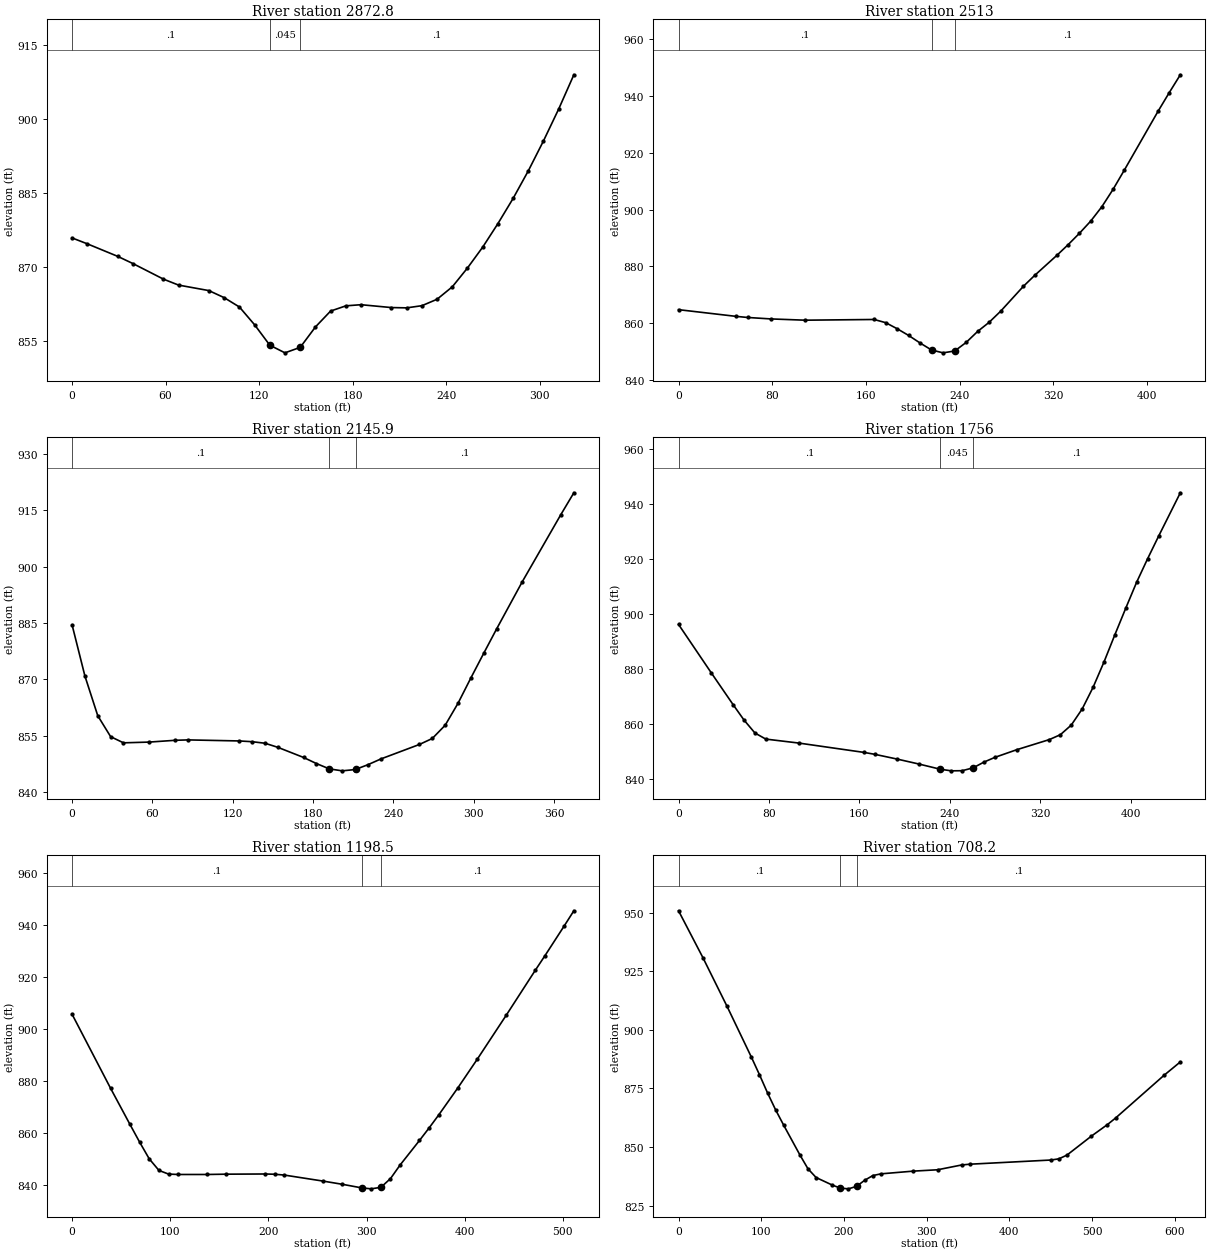
Type RM Length L Ch R = 1 ,2872.8  ,376.1,359.8,343.2
XS GIS Cut Line= 2
     1899904.708      461185.283     1900107.368      460934.994
#Sta/Elev= 30
       0  875.84     9.8  874.64    29.3   872.1      39  870.65    58.6  867.49
    68.3  866.28    87.8  865.16    97.6  863.73   107.4  861.83   117.1  858.24
   126.9  854.09   136.6  852.54   146.4  853.65   156.2   857.8   165.9  861.01
   175.7  862.07   185.4   862.3   204.9  861.72   214.7  861.66   224.5   862.1
   234.2   863.4     244  865.93   253.7  869.73   263.5  873.97   273.2  878.71
     283  883.84   292.8  889.46   302.5  895.51   312.3     902     322  908.92
#Mann= 3 , 0 , 0
       0      .1       0   126.9    .045       0   146.4      .1       0
Bank Sta=126.9,146.4
XS Rating Curve= 0 ,0
Exp/Cntr=0.3,0.1

Type RM Length L Ch R = 1 ,2513    ,380.9,367.1,352.6
XS GIS Cut Line= 3
     1900340.423      461397.501     1900326.932      461113.053
     1900331.508      460969.549
#Sta/Elev= 30
       0  864.69    49.1  862.33    58.9  861.94    78.6  861.43     108  860.98
   166.9  861.23   176.8  860.11   186.6  857.97   196.4   855.6   206.2  852.93
     216  850.46   225.8  849.47   235.7  850.12   236.2  850.27   245.5  853.14
   255.3  857.02   265.1  860.23     275  864.17   294.3   872.9   303.9  876.74
   323.1  883.91   332.6  887.63   342.2  891.62   351.8  895.91   361.3  900.97
   370.9  907.11   380.5  913.89   409.2  934.57   418.8  941.18   428.3   947.5
#Mann= 3 , 0 , 0
       0      .1       0     216    .045       0   236.2      .1       0
Bank Sta=216,236.2
XS Rating Curve= 0 ,0
Exp/Cntr=0.3,0.1

Type RM Length L Ch R = 1 ,2145.9  ,389.4,389.9,390
XS GIS Cut Line= 2
     1900761.753      461137.018      1900527.74      460844.429
#Sta/Elev= 30
       0  884.51     9.6   870.9    19.2  860.35    28.8   854.8    38.4  853.16
    57.6  853.36    76.8  853.83    86.5  853.94   124.9  853.66   134.5  853.46
   144.1  853.05   153.7  851.96   172.9  849.27   182.5  847.65   192.1  846.24
   201.7  845.72   211.4  846.06   212.2  846.17     221  847.36   230.6  848.88
   259.4  852.73     269  854.32   278.6  857.83   288.2  863.67   297.8   870.4
   307.4  876.95     317  883.41   336.2  895.97     365   913.8   374.7  919.59
#Mann= 3 , 0 , 0
       0      .1       0   192.1    .045       0   212.2      .1       0
Bank Sta=192.1,212.2
XS Rating Curve= 0 ,0
Exp/Cntr=0.3,0.1

Type RM Length L Ch R = 1 ,1756    ,555,557.5,559.8
XS GIS Cut Line= 2
     1901084.711      460923.046      1900812.63      460572.264
#Sta/Elev= 30
       0  896.06      29  878.44    48.2  866.94    57.9  861.31    67.6  856.58
    77.2  854.37   106.2  852.94   164.1  849.53   173.7  848.83     193  847.14
   212.3  845.34   231.6  843.41   241.3  842.83   250.9  842.88   260.6  843.92
   270.2  846.01   279.9  847.74   299.2  850.51   328.1   854.2   337.8  855.97
   347.4  859.45   357.1  865.34   366.7  873.18   376.4  882.43     386  892.31
   395.7  902.04   405.3  911.45     415  919.98   424.6  928.07   443.9  943.92
#Mann= 3 , 0 , 0
       0      .1       0   231.6    .045       0   260.6      .1       0
Bank Sta=231.6,260.6
XS Rating Curve= 0 ,0
Exp/Cntr=0.3,0.1

Type RM Length L Ch R = 1 ,1198.5  ,487.7,490.2,492.2
XS GIS Cut Line= 2
     1901510.821      460649.841     1901244.361      460213.612
#Sta/Elev= 30
       0   905.6    39.3  877.03      59  863.15    68.8  856.36    78.6  849.91
    88.5  845.45    98.3  844.03   108.1  843.88   137.6  843.88   157.3     844
   196.6  844.07   206.4  843.97   216.3  843.65   255.6  841.34   275.2  840.11
   294.9  838.73   304.7  838.35   314.6  838.93   324.4   842.3   334.2  847.54
   353.9  856.97   363.7  861.79   373.6  866.85   393.2  877.34   412.9  888.34
   442.4  905.27   471.8  922.47   481.7  928.12   501.3  939.57   511.2  945.45
#Mann= 3 , 0 , 0
       0      .1       0   294.9    .045       0   314.6      .1       0
Bank Sta=294.9,314.6
XS Rating Curve= 0 ,0
Exp/Cntr=0.3,0.1

Type RM Length L Ch R = 1 ,708.2   ,440.6,430.5,420.2
XS GIS Cut Line= 2
     1901914.204      460461.839     1901651.308      459915.208
#Sta/Elev= 30
       0  950.87    29.4   930.9    58.7  910.02      88  888.42    97.8   880.9
   107.6  873.09   117.4  865.83   127.2  859.25   146.8  846.56   156.5  840.68
   166.3  836.96   185.9  833.73   195.7  832.43   205.4  832.13   215.2  833.19
     225  835.78   234.8  837.79   244.6  838.53   283.7  839.69   313.1  840.27
   342.4  842.33   352.2  842.65     450  844.43   459.8  844.94   469.6  846.55
     499  854.62   518.5  859.58   528.3  862.36     587  880.64   606.6  886.33
#Mann= 3 , 0 , 0
       0      .1       0   195.7    .045       0   215.2      .1       0
Bank Sta=195.7,215.2
XS Rating Curve= 0 ,0
Exp/Cntr=0.3,0.1

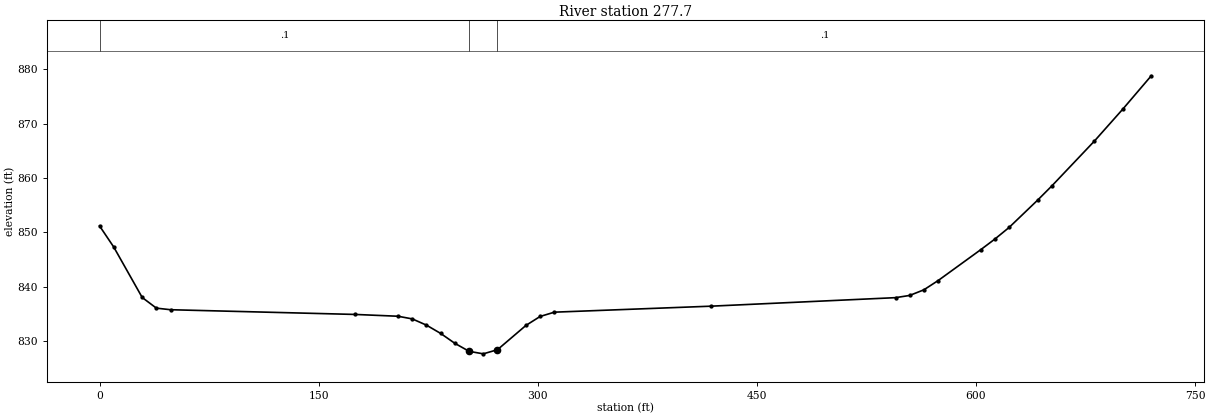
Type RM Length L Ch R = 1 ,277.7   ,278.2,277.7,277.3
XS GIS Cut Line= 2
     1902358.241      460168.486     1901793.977      459721.243
#Sta/Elev= 30
       0   851.2     9.7  847.32    29.2  838.03    38.9  836.07    48.6  835.78
   175.1  834.91   204.3  834.58   214.1  834.09   223.8  832.94   233.5  831.42
   243.2   829.6     253  828.12   262.7  827.66   272.4  828.42   291.9  832.89
   301.6  834.54   311.4  835.33   418.4  836.43   544.9     838   554.6  838.41
   564.3  839.44   574.1  841.15   603.3  846.84     613   848.8   622.7  850.93
   642.2  855.95   651.9  858.56   681.1  866.83   700.6  872.73     720  878.84
#Mann= 3 , 0 , 0
       0      .1       0     253    .045       0   272.4      .1       0
Bank Sta=253,272.4
XS Rating Curve= 0 ,0
Exp/Cntr=0.3,0.1

Chan Stop Cuts=-1
Use User Specified Reach Order=0
Composite Channel Slope=5